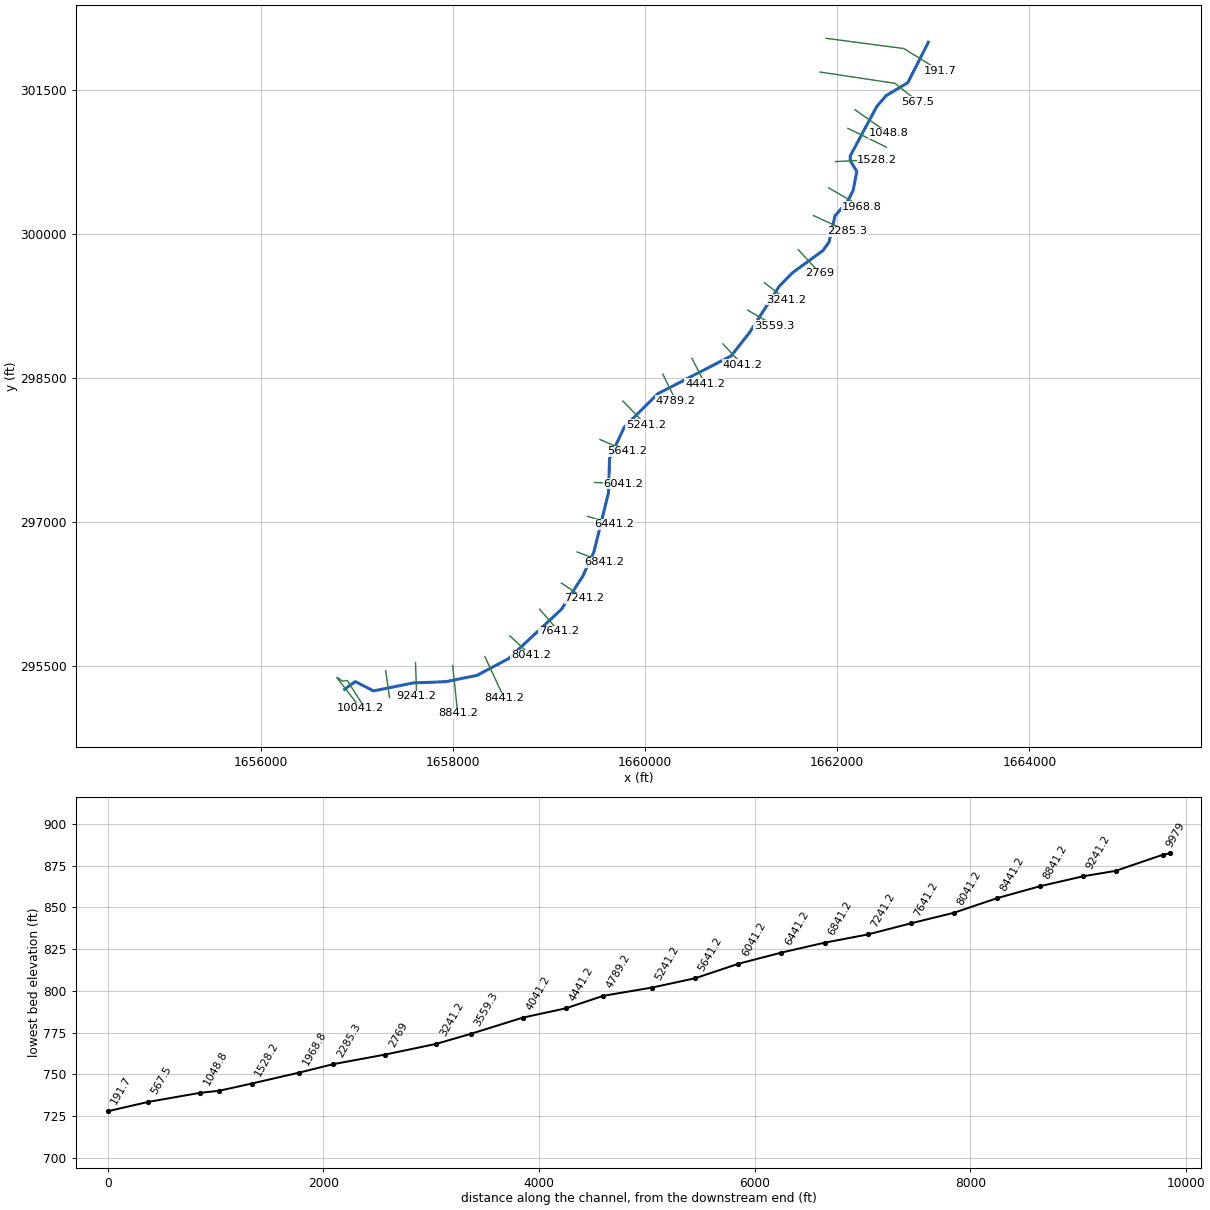
--- TRACEFRK2.prj (project) ---

Proj Title=TRACEFRK2
Current Plan=p01
Default Exp/Contr=0,0
English Units
Geom File=g01
Flow File=f01
Plan File=p01
BEGIN DESCRIPTION:
END DESCRIPTION:
DSS Export Rating Curves= 0
DSS Export Rating Curve Sorted= 0
DSS Export Volume Flow Curves= 0
DXF OffsetX= 0
DXF OffsetY= 0
DXF ScaleX= 0
DXF ScaleY= 0

--- TRACEFRK2.p01 (plan) ---

Plan Title=Floodplain
Program Version=4.00
Geom File=g01
Flow File=f01
K Sum by GR=0
Std Step Tol=0.01
Critical Tol=0.01
Num of Std Step Trials=20
Max Error Tol=0.3
Flow Tol Ratio=0.001
Split Flow NTrial=30
Split Flow Tol=0.02
Split Flow Ratio=0.02
Log Output Level=0
Friction Slope Method=1
Unsteady Friction Slope Method=2
Unsteady Bridges Friction Slope Method=1
Global Log Level=0
CheckData=False
Run HTab=0
Run UNet=0
Run PostProcess=0
UNET Theta=0
UNET Theta Warmup=0
UNET ZTol=0
UNET ZSATol=0
UNET MxIter=0
UNET MaxInSteps=0
UNET DtIC=0
UNET DtMin=0
UNET MaxCRTS=0
UNET WFStab=0
UNET SFStab=0
UNET WFX=0
UNET SFX=0
UNET DSS MLevel=0
UNET DZMax Abort=0
UNET Convert EG Bridges=0
UNET Use Existing IB Tables=0
UNET Froude Limit=0
UNET Froude Power=0
Write IC File=0
Echo Input=False
Echo Output=False
Write Detailed=0

--- TRACEFRK2.f01 (steady flow) ---

Flow Title=NFF Regression Equation
Program Version=4.00
Number of Profiles=1
Profile Names=P100yr
River Rch & RM=TRACEFRK2,Main      ,10041.2
1021.752
River Rch & RM=TRACEFRK2,Main      ,8441.2
1046.799
River Rch & RM=TRACEFRK2,Main      ,8041.2
1225.039
River Rch & RM=TRACEFRK2,Main      ,6841.2
1250.553
River Rch & RM=TRACEFRK2,Main      ,5241.2
1389.082
River Rch & RM=TRACEFRK2,Main      ,2285.3
1467.646
River Rch & RM=TRACEFRK2,Main      ,191.7
1564.793
Boundary for River Rch & Prof#=TRACEFRK2,Main      ,1
Up Type=0
Dn Type=3
Dn Slope=0.011031

--- TRACEFRK2.g01 (geometry) ---

Geom Title=USGS 10m DEM
Program Version=4.10

River Reach=TRACEFRK2       ,Main
Reach XY= 30
     1656873.786      295254.795     1656984.974      295334.711
     1657173.761      295237.422     1657588.398      295320.813
     1657926.593      295333.553     1658252.048      295399.571
     1658578.661      295573.301     1659128.808      296087.543
     1659352.341      296433.846     1659468.161      296687.493
     1659619.886      297305.973      1659630.31      297659.225
     1659784.351      297989.313     1660130.653      298335.616
     1660895.068      298730.563     1661085.013      298971.469
     1661396.569      299457.915     1661533.237      299598.057
     1661850.585      299829.698     1661914.286      299917.721
     1661976.829      300191.057     1662111.181      300348.573
     1662165.616      300457.444     1662203.837      300655.496
     1662134.345         300769.     1662135.503      300817.645
     1662412.313      301334.203     1662509.603      301446.549
     1662734.294      301580.901     1662948.398      302002.941

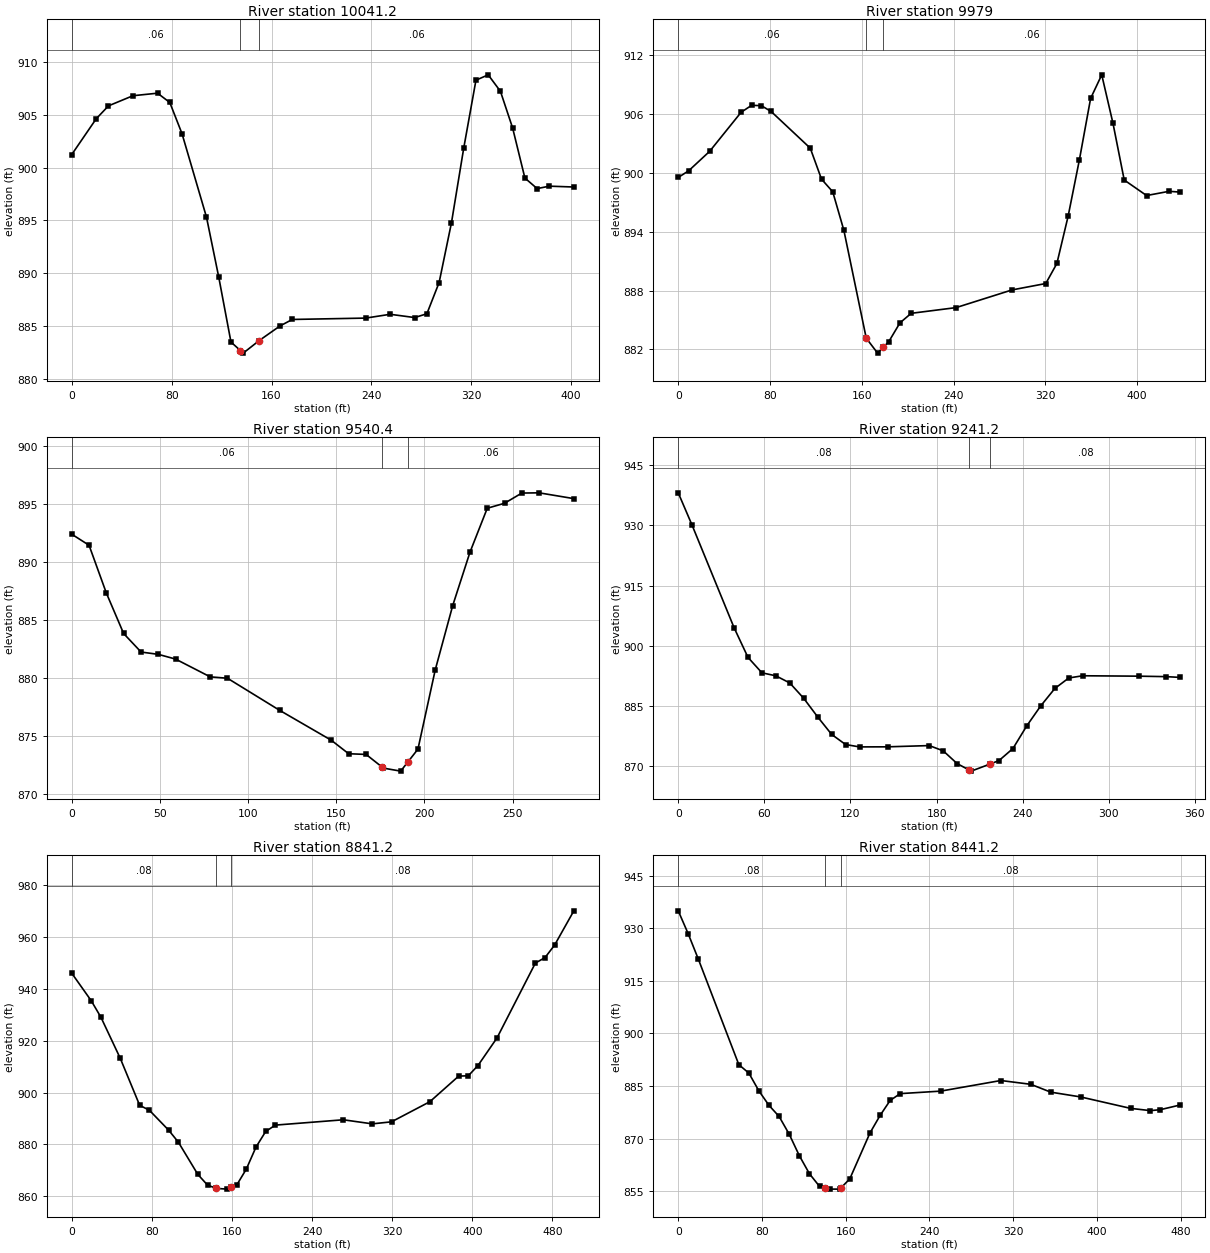
Type RM Length L Ch R = 1 ,10041.2 ,64.2,62.2,60.2
XS GIS Cut Line= 2
     1656794.626      295373.869     1657040.135      295055.372
#Sta/Elev= 30
       0  901.25    19.6  904.64    29.4  905.86      49  906.82    68.7  907.06
    78.5  906.18    88.3  903.22   107.9  895.31   117.7  889.64   127.5  883.48
   135.1  882.67   137.3  882.43   150.1  883.62   166.7     885   176.6  885.62
   235.4  885.75     255  886.11   274.6   885.8   284.4  886.16   294.2  889.12
   304.1  894.79   313.9  901.85   323.7  908.29   333.5   908.8   343.3  907.24
   353.1  903.75   362.9  899.02   372.7  898.02   382.5  898.25   402.1  898.17
#Mann= 3 , 0 , 0
       0     .06       0   135.1    .045       0   150.1     .06       0
Bank Sta=135.1,150.1
XS Rating Curve= 0 ,0
Exp/Cntr=0.3,0.1

Type RM Length L Ch R = 1 ,9979    ,449.7,438.5,426.7
XS GIS Cut Line= 4
     1656798.192      295376.759      1656850.01      295339.288
     1656900.691      295346.378     1657073.984      295074.351
#Sta/Elev= 30
       0   899.5     9.1  900.18    27.4  902.16    54.8  906.13      64  906.84
    72.5   906.8      81  906.21   115.1  902.48   124.9  899.33   134.7  898.04
   144.4  894.12   163.9  883.15   173.8  881.63   178.9  882.24   183.5  882.79
   193.3  884.71   203.1  885.68   242.2  886.26     291  888.06   320.4  888.71
   330.1  890.75   339.9  895.56   349.7  901.28   359.5  907.54   369.2  909.94
     379  905.01   388.8  899.24   408.3  897.66   427.9  898.09   437.7  898.01
#Mann= 3 , 0 , 0
       0     .06       0   163.9    .045       0   178.9     .06       0
Bank Sta=163.9,178.9
XS Rating Curve= 0 ,0
Exp/Cntr=0.3,0.1

Type RM Length L Ch R = 1 ,9540.4  ,301.4,299.1,296.9
XS GIS Cut Line= 2
     1657300.804      295449.734      1657341.11      295167.945
#Sta/Elev= 26
       0  892.39     9.8  891.44    19.6  887.32    29.4  883.83    39.3  882.23
    49.1  882.03    58.9  881.62    78.5  880.09    88.3  879.97   117.8  877.21
   147.2  874.62     157  873.46   166.9   873.4   175.8  872.33   176.7  872.22
   186.5  871.96   190.8  872.79   196.3  873.86   206.1  880.69     216  886.23
   225.8  890.84   235.6  894.63   245.4  895.06   255.2  895.94     265  895.96
   284.7  895.46
#Mann= 3 , 0 , 0
       0     .06       0   175.8    .045       0   190.8     .06       0
Bank Sta=175.8,190.8
XS Rating Curve= 0 ,0
Exp/Cntr=0.3,0.1

Type RM Length L Ch R = 1 ,9241.2  ,398.3,399.9,401.5
XS GIS Cut Line= 2
     1657611.879      295532.682     1657623.147      295183.046
#Sta/Elev= 29
       0  938.14     9.7  930.03    38.9  904.51    48.6   897.1    58.3  893.26
      68  892.51    77.7  890.73    87.4  886.91    97.2  882.23   106.9  877.89
   116.6  875.37   126.3  874.78   145.8   874.8   174.9  875.11   184.6   873.8
   194.3  870.62   202.5  869.05   204.1  868.74   217.5  870.54   223.5  871.38
   233.2  874.38   242.9  880.07   252.6  885.03   262.4  889.36   272.1  891.97
   281.8  892.52   320.7  892.42   340.1   892.3   349.8  892.11
#Mann= 3 , 0 , 0
       0     .08       0   202.5    .045       0   217.5     .08       0
Bank Sta=202.5,217.5
XS Rating Curve= 0 ,0
Exp/Cntr=0.3,0.1

Type RM Length L Ch R = 1 ,8841.2  ,392.4,399.9,407.3
XS GIS Cut Line= 3
     1657998.022      295501.725     1658028.526      295212.772
     1658050.659      295003.113
#Sta/Elev= 30
       0  945.94    19.4  935.37    29.1     929    48.4   913.2    67.8  895.08
    77.5  893.17    96.8  885.48   106.5  880.85   125.9  868.45   135.6  864.34
   144.3  863.08     155  862.79   159.3  863.46   164.6  864.28   174.3   870.5
     184     879   193.7  885.02   203.4  887.45   271.2   889.5   300.1  887.93
   319.3  888.71   357.6  896.46   386.4  906.32     396  906.45   405.6  910.37
   424.7  921.05     463  949.87   472.6  951.96   482.2  956.79   501.4  969.98
#Mann= 3 , 0 , 0
       0     .08       0   144.3    .045       0   159.3     .08       0
Bank Sta=144.3,159.3
XS Rating Curve= 0 ,0
Exp/Cntr=0.3,0.1

Type RM Length L Ch R = 1 ,8441.2  ,391.2,400,408.7
XS GIS Cut Line= 3
     1658333.743      295594.393     1658455.565      295332.006
     1658535.787       295159.22
#Sta/Elev= 30
       0  934.96     9.6  928.36    19.3  921.11    57.9  891.09    67.5  888.67
    77.1  883.59    86.8  879.44    96.4   876.3   106.1  871.22   115.7  865.13
   125.4  859.96     135  856.37   140.5  855.92   144.6  855.59   154.3  855.58
   155.5  855.94   163.9  858.48   183.2  871.58   192.9   876.6   202.5  880.87
   212.1  882.82   250.7  883.53   308.3  886.56   336.9  885.48     356  883.24
   384.5  881.88   432.2  878.62   451.2  877.97   460.7  878.24   479.8  879.59
#Mann= 3 , 0 , 0
       0     .08       0   140.5    .045       0   155.5     .08       0
Bank Sta=140.5,155.5
XS Rating Curve= 0 ,0
Exp/Cntr=0.3,0.1

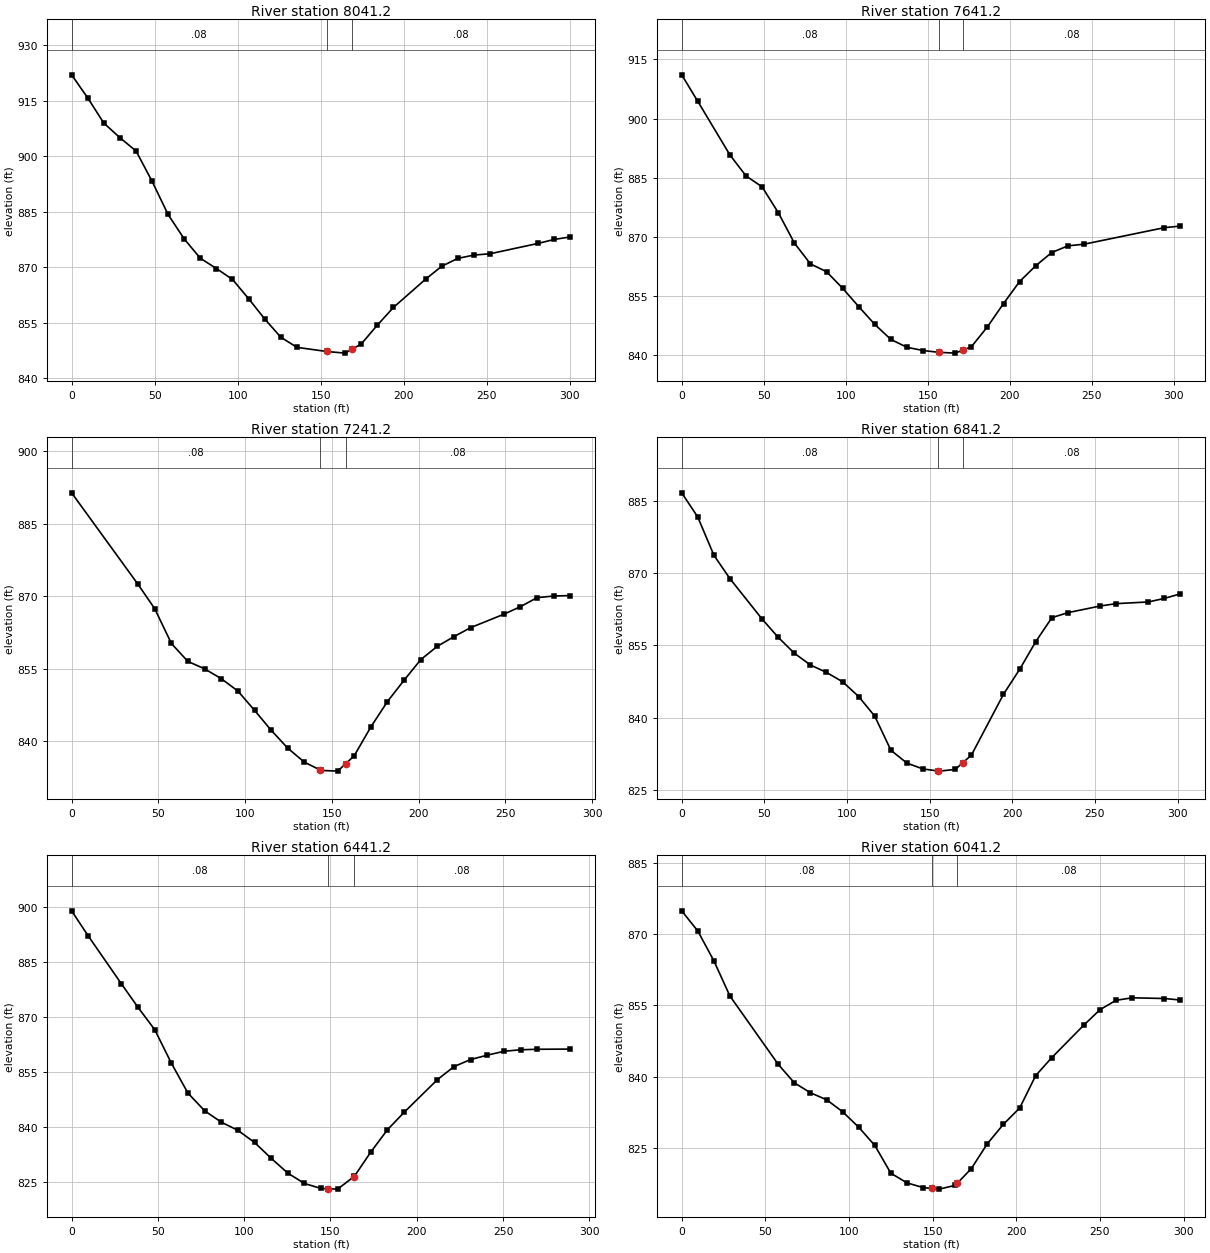
Type RM Length L Ch R = 1 ,8041.2  ,402.4,399.9,397.4
XS GIS Cut Line= 2
     1658592.751      295811.536     1658812.762      295606.984
#Sta/Elev= 29
       0  921.96     9.7  915.74    19.4  908.94    29.1  904.99    38.8   901.4
    48.4  893.29    58.1  884.26    67.8  877.68    77.5  872.46    87.2  869.68
    96.9  866.73   106.6  861.54   116.3  856.06     126  851.13   135.7   848.4
   153.7  847.28   164.7  846.84   168.7  847.85   174.4  849.28   184.1  854.38
   193.8  859.16   213.2   866.8   222.9  870.29   232.6  872.41   242.3  873.31
     252  873.66     281  876.46   290.7  877.53   300.4  878.21
#Mann= 3 , 0 , 0
       0     .08       0   153.7    .045       0   168.7     .08       0
Bank Sta=153.7,168.7
XS Rating Curve= 0 ,0
Exp/Cntr=0.3,0.1

Type RM Length L Ch R = 1 ,7641.2  ,393.9,399.9,406
XS GIS Cut Line= 2
     1658903.244      296089.299     1659102.015      295859.102
#Sta/Elev= 28
       0  911.09     9.8  904.37    29.4  890.77    39.2  885.45      49  882.68
    58.9  876.12    68.7  868.42    78.5  863.12    88.3  861.15    98.1  856.96
   107.9   852.3   117.7  847.79   127.5  843.97   137.4  841.96   147.2  841.15
   156.6   840.7   166.8  840.49   171.6  841.28   176.6   842.1   186.4  847.16
   196.2  853.06     206  858.64   215.8  862.64   225.6  866.01   235.5  867.71
   245.3  868.12   294.3  872.32   304.1  872.72
#Mann= 3 , 0 , 0
       0     .08       0   156.6    .045       0   171.6     .08       0
Bank Sta=156.6,171.6
XS Rating Curve= 0 ,0
Exp/Cntr=0.3,0.1

Type RM Length L Ch R = 1 ,7241.2  ,394.7,399.9,405.1
XS GIS Cut Line= 2
     1659130.059      296362.149     1659368.733      296202.118
#Sta/Elev= 29
       0  891.42    38.3  872.46    47.9  867.43    57.5  860.23      67  856.52
    76.6  854.99    86.2  852.96    95.8  850.39   105.4   846.4   114.9  842.31
   124.5  838.58   134.1  835.67     143  834.08   143.7  833.96   153.3  833.81
     158  835.37   162.8  836.97   172.4  842.94     182  848.22   191.6  852.64
   201.2   856.9   210.7  859.64   220.3  861.65   229.9  863.51     249  866.28
   258.6  867.85   268.2  869.72   277.8  870.06   287.4  870.16
#Mann= 3 , 0 , 0
       0     .08       0     143    .045       0     158     .08       0
Bank Sta=143,158
XS Rating Curve= 0 ,0
Exp/Cntr=0.3,0.1

Type RM Length L Ch R = 1 ,6841.2  ,398.6,400,401.4
XS GIS Cut Line= 2
     1659293.913      296686.226     1659576.335      296579.705
#Sta/Elev= 30
       0  886.64     9.7  881.64    19.5  873.68    29.2  868.83    48.7  860.43
    58.4  856.66    68.2  853.35    77.9  850.92    87.6  849.38    97.4  847.43
   107.1  844.37   116.8  840.31   126.6  833.22   136.3  830.56     146  829.35
   155.1  828.93   155.8   828.9   165.5  829.25   170.1  830.64   175.3  832.22
   194.7  844.84   204.5  850.02   214.2  855.75     224  860.74   233.7  861.78
   253.2  863.16   262.9  863.65   282.4     864   292.1  864.74   301.8  865.69
#Mann= 3 , 0 , 0
       0     .08       0   155.1    .045       0   170.1     .08       0
Bank Sta=155.1,170.1
XS Rating Curve= 0 ,0
Exp/Cntr=0.3,0.1

Type RM Length L Ch R = 1 ,6441.2  ,394.4,399.9,405.5
XS GIS Cut Line= 2
     1659401.827      297058.426     1659678.197      296973.864
#Sta/Elev= 30
       0  898.97     9.6  892.14    28.9     879    38.5   872.6    48.2  866.48
    57.8  857.36    67.4  849.19    77.1  844.35    86.7  841.26    96.3  839.03
     106   835.7   115.6   831.4   125.2  827.36   134.9   824.5   144.5  823.14
   148.5  823.06   154.1  822.96   163.5  826.32   163.8  826.43   173.4  833.12
     183  839.18   192.7  843.95     212  852.89   221.6  856.43   231.2  858.36
   240.8  859.54   250.5  860.61   260.1  861.02   269.8  861.16     289  861.21
#Mann= 3 , 0 , 0
       0     .08       0   148.5    .045       0   163.5     .08       0
Bank Sta=148.5,163.5
XS Rating Curve= 0 ,0
Exp/Cntr=0.3,0.1

Type RM Length L Ch R = 1 ,6041.2  ,408.2,399.9,391.7
XS GIS Cut Line= 2
     1659475.411      297411.447     1659773.151      297396.485
#Sta/Elev= 30
       0  874.96     9.6  870.72    19.2  864.44    28.8     857    57.7  842.56
    67.3  838.68    76.9  836.58    86.6   835.1    96.2  832.56   105.8   829.3
   115.4  825.47     125   819.6   134.6  817.57   144.2  816.57   149.8  816.38
   153.9  816.24   163.5  817.04   164.8  817.52   173.1  820.57   182.7  825.84
   192.3  829.93     202  833.36   211.6  840.21   221.2  843.99   240.4  850.87
     250   854.1   259.6  856.08   269.3  856.61   288.5  856.46   298.1  856.14
#Mann= 3 , 0 , 0
       0     .08       0   149.8    .045       0   164.8     .08       0
Bank Sta=149.8,164.8
XS Rating Curve= 0 ,0
Exp/Cntr=0.3,0.1

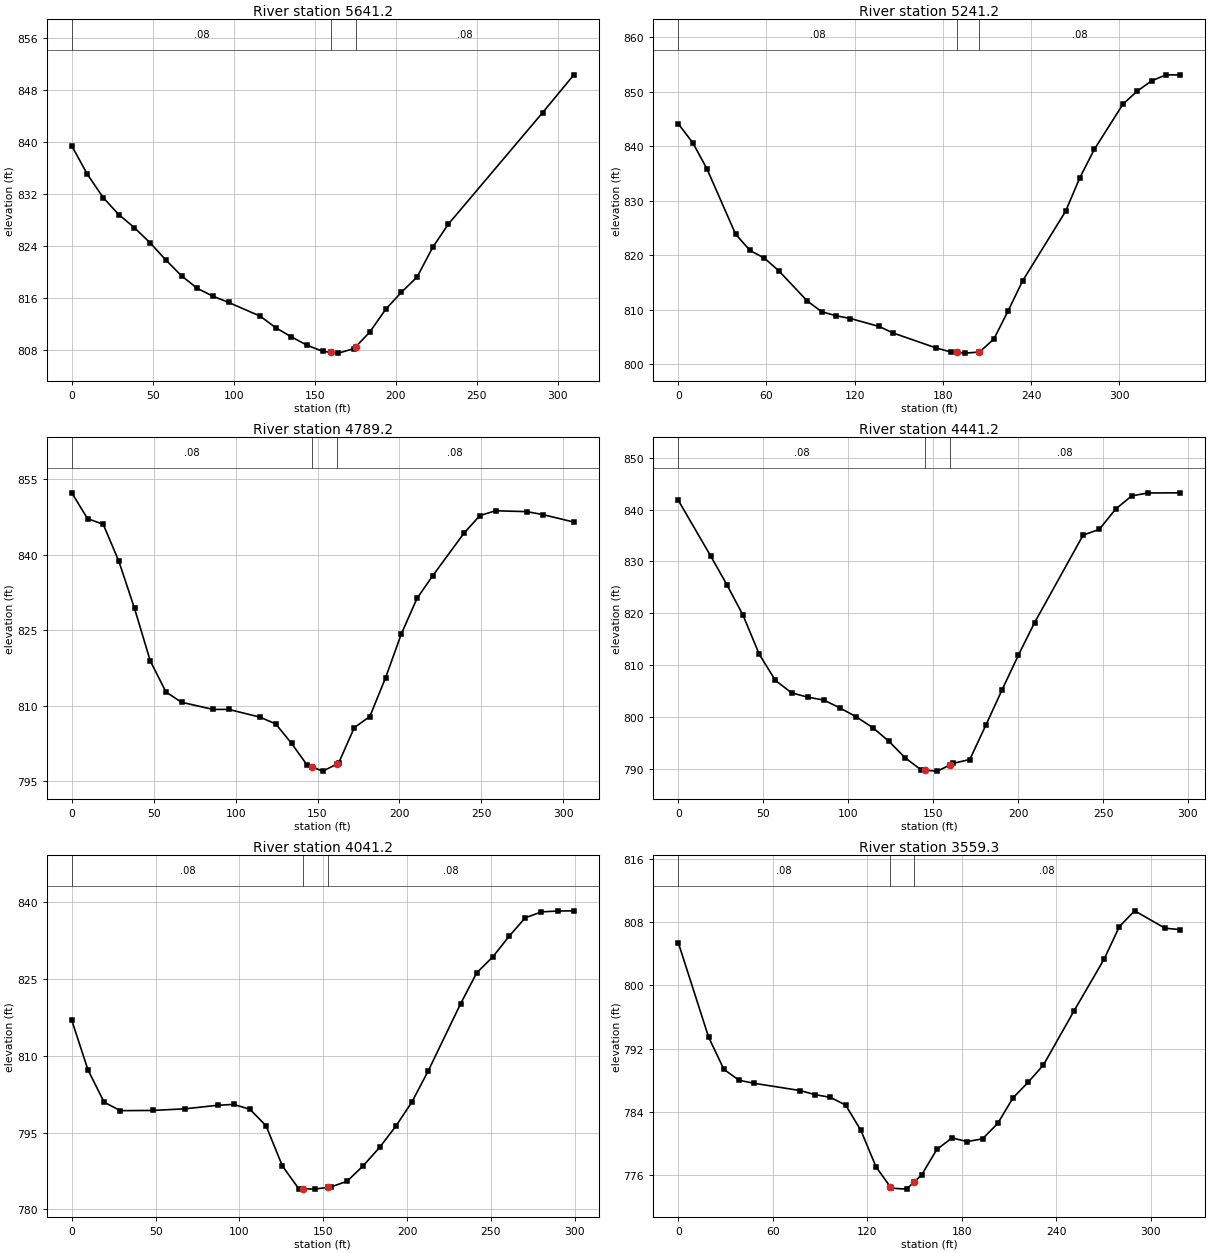
Type RM Length L Ch R = 1 ,5641.2  ,408.8,400,391.2
XS GIS Cut Line= 2
     1659530.156      297860.169     1659813.636      297734.911
#Sta/Elev= 28
       0  839.46     9.7  835.06    19.4   831.5      29   828.9    38.7  826.87
    48.4  824.53    58.1   821.9    67.8  819.46    77.5  817.54    87.2  816.33
    96.8  815.38   116.2  813.28   125.9  811.49   135.6  810.07   145.3  808.79
     155  807.84   160.3   807.7   164.6  807.58   174.3  808.29   175.3  808.55
     184  810.84   193.7   814.3   203.4  816.93   213.1  819.27   222.8  823.86
   232.4  827.41   290.6  844.57   309.9  850.39
#Mann= 3 , 0 , 0
       0     .08       0   160.3    .045       0   175.3     .08       0
Bank Sta=160.3,175.3
XS Rating Curve= 0 ,0
Exp/Cntr=0.3,0.1

Type RM Length L Ch R = 1 ,5241.2  ,459,451.9,444.9
XS GIS Cut Line= 2
      1659770.12      298260.039     1660007.274      298014.415
#Sta/Elev= 30
       0  844.14     9.8  840.68    19.5  835.87      39  823.85    48.8  820.85
    58.5  819.46    68.3  817.14    87.8  811.55    97.6  809.59   107.3  808.86
   117.1  808.35   136.6  806.89   146.3  805.67   175.6  802.92   185.4   802.2
   189.4  802.11   195.1  801.99   204.4  802.19   204.9   802.2   214.6  804.57
   224.4   809.8   234.1  815.24   263.4  828.06   273.1  834.24   282.9  839.42
   302.4  847.74   312.2  850.16   321.9  852.02   331.7  853.13   341.4   853.1
#Mann= 3 , 0 , 0
       0     .08       0   189.4    .045       0   204.4     .08       0
Bank Sta=189.4,204.4
XS Rating Curve= 0 ,0
Exp/Cntr=0.3,0.1

Type RM Length L Ch R = 1 ,4789.2  ,347.6,348,348.5
XS GIS Cut Line= 2
     1660185.783       298540.25     1660320.474      298265.012
#Sta/Elev= 30
       0  852.33     9.6  847.21    19.2  846.07    28.7  838.77    38.3  829.36
    47.9  818.94    57.5  812.76      67  810.72    86.2   809.3    95.8   809.3
   114.9  807.76   124.5  806.42   134.1  802.56   143.6  798.25   146.7  797.86
   153.2  797.04   161.7  798.42   162.8   798.6   172.4  805.68   181.9  807.89
   191.5  815.59   201.1  824.28   210.7  831.37   220.2  835.82   239.4  844.33
     249   847.8   258.6  848.77   277.7  848.59   287.3  848.02   306.4  846.52
#Mann= 3 , 0 , 0
       0     .08       0   146.7    .045       0   161.7     .08       0
Bank Sta=146.7,161.7
XS Rating Curve= 0 ,0
Exp/Cntr=0.3,0.1

Type RM Length L Ch R = 1 ,4441.2  ,393.7,400,406.3
XS GIS Cut Line= 2
     1660488.007      298705.471     1660623.456      298442.866
#Sta/Elev= 30
       0   841.8    19.1  831.03    28.6  825.51    38.1  819.64    47.7  812.07
    57.2  807.04    66.7  804.64    76.2  803.81    85.8  803.24    95.3   801.7
   104.8  800.01   114.4  797.95   123.9  795.33   133.4  792.15     143  789.77
     145  789.72   152.5  789.54     160  790.74     162  791.06   171.6  791.78
   181.1  798.44   190.6  805.23   200.2  811.91   209.7  818.17   238.3  835.06
   247.8  836.17   257.4  840.07   266.9  842.63   276.4  843.19   295.5  843.22
#Mann= 3 , 0 , 0
       0     .08       0     145    .045       0     160     .08       0
Bank Sta=145,160
XS Rating Curve= 0 ,0
Exp/Cntr=0.3,0.1

Type RM Length L Ch R = 1 ,4041.2  ,475.3,481.8,488.4
XS GIS Cut Line= 2
     1660809.237      298856.909     1661014.649      298638.928
#Sta/Elev= 30
       0  816.93     9.7  807.22    19.3  800.93      29  799.28    48.3  799.32
    67.6  799.64      87  800.33    96.6   800.5   106.3  799.54   115.9  796.32
   125.6   788.5   135.3  784.05   138.1  784.02   144.9  783.94   153.1   784.3
   154.6  784.37   164.2  785.47   173.9  788.52   183.6  792.09   193.2  796.19
   202.9  800.97   212.6  807.03   231.9  820.15   241.6  826.24   251.2  829.35
   260.9  833.37   270.5  836.98   280.2  838.13   289.8   838.3   299.5  838.34
#Mann= 3 , 0 , 0
       0     .08       0   138.1    .045       0   153.1     .08       0
Bank Sta=138.1,153.1
XS Rating Curve= 0 ,0
Exp/Cntr=0.3,0.1

Type RM Length L Ch R = 1 ,3559.3  ,321.1,318.1,315.1
XS GIS Cut Line= 2
     1661068.364      299208.546     1661344.134      299048.422
#Sta/Elev= 30
       0  805.43    19.3  793.45      29  789.38    38.6     788    48.3  787.61
    77.3   786.7      87  786.17    96.6  785.84   106.3  784.86     116  781.66
   125.6  777.05   134.6  774.54   135.3  774.34     145  774.22   149.6  775.08
   154.6  776.02   164.3  779.26   173.9  780.69   183.6  780.24   193.3  780.59
   202.9  782.53   212.6  785.76   222.2  787.74   231.9  789.91   251.2  796.71
   270.6  803.36   280.2  807.45   289.9  809.44   309.2  807.24   318.9  807.06
#Mann= 3 , 0 , 0
       0     .08       0   134.6    .045       0   149.6     .08       0
Bank Sta=134.6,149.6
XS Rating Curve= 0 ,0
Exp/Cntr=0.3,0.1

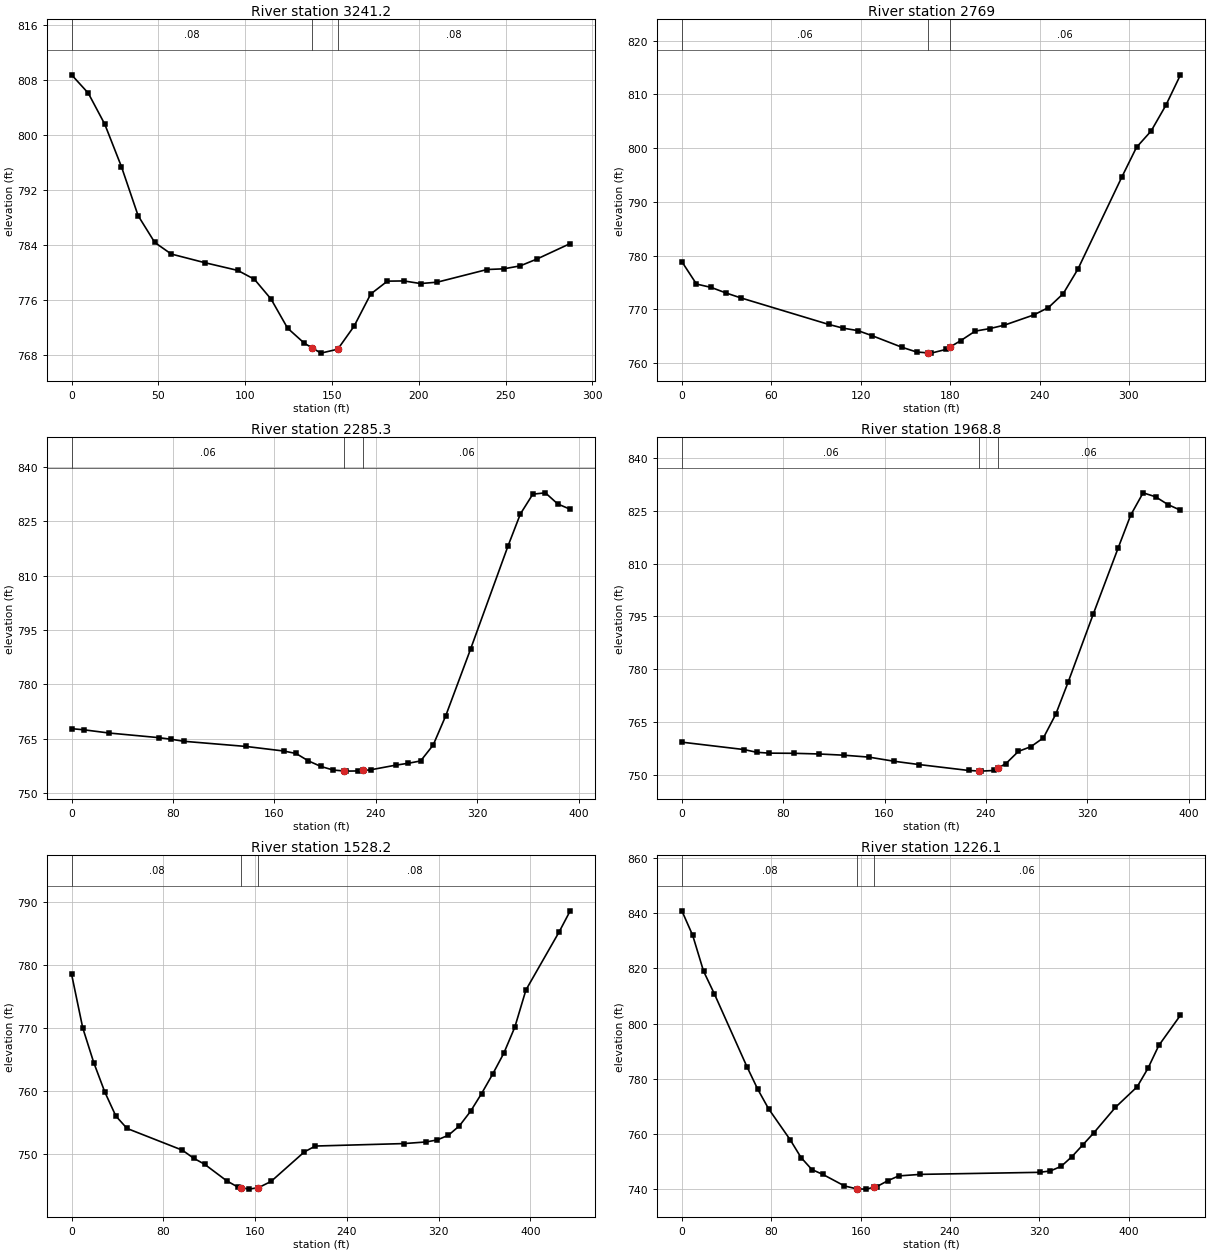
Type RM Length L Ch R = 1 ,3241.2  ,476.2,472.4,468.6
XS GIS Cut Line= 2
     1661243.046      299494.232     1661470.303      299318.685
#Sta/Elev= 27
       0  808.69     9.6  806.03    19.1  801.52    28.7  795.35    38.3  788.23
    47.9  784.33    57.4  782.65    76.6   781.4    95.7  780.27   105.3  778.98
   114.9   776.1   124.4  771.88     134   769.7   138.3  769.05   143.6  768.25
   153.3  768.82   162.7  772.16   172.3  776.84   181.9  778.71   191.4  778.74
     201  778.36   210.6  778.56   239.3   780.4   248.9   780.5   258.4  780.93
     268  781.92   287.2  784.17
#Mann= 3 , 0 , 0
       0     .08       0   138.3    .045       0   153.3     .08       0
Bank Sta=138.3,153.3
XS Rating Curve= 0 ,0
Exp/Cntr=0.3,0.1

Type RM Length L Ch R = 1 ,2769    ,474.5,483.6,492.6
XS GIS Cut Line= 2
     1661593.454      299839.769     1661819.875        299593.4
#Sta/Elev= 28
       0  778.86     9.8   774.7    19.7  774.07    29.5  773.05    39.4  772.14
    98.4   767.2   108.3  766.49   118.1  766.04   127.9  765.07   147.6  762.95
   157.5  762.06     165   761.9   167.3  761.85   177.2  762.54     180     763
     187  764.15   196.8  765.94   206.7  766.42   216.5  767.06   236.2  768.96
     246  770.33   255.9  772.91   265.7  777.44   295.2  794.58   305.1  800.14
   314.9  803.17   324.8  807.96   334.6  813.62
#Mann= 3 , 0 , 0
       0     .06       0     165    .045       0     180     .06       0
Bank Sta=165,180
XS Rating Curve= 0 ,0
Exp/Cntr=0.3,0.1

Type RM Length L Ch R = 1 ,2285.3  ,318.3,316.2,314.1
XS GIS Cut Line= 2
     1661751.251      300195.918     1662108.742      300031.879
#Sta/Elev= 29
       0  767.78     9.8  767.46    29.5  766.58    68.8   765.3    78.7  764.85
    88.5   764.3   137.7  762.87   167.2  761.62     177  760.94   186.8  758.89
   196.7  757.35   206.5  756.36   215.1  756.11   216.3  756.07   226.2  756.12
   230.1  756.25     236  756.44   255.7  757.72   265.5  758.23   275.3  758.88
   285.2  763.26     295  771.23   314.7  789.71   344.2  818.12     354  826.99
   363.8  832.44   373.7  832.81   383.5  829.73   393.3  828.28
#Mann= 3 , 0 , 0
       0     .06       0   215.1    .045       0   230.1     .06       0
Bank Sta=215.1,230.1
XS Rating Curve= 0 ,0
Exp/Cntr=0.3,0.1

Type RM Length L Ch R = 1 ,1968.8  ,427.9,440.4,452.7
XS GIS Cut Line= 2
     1661910.127      300484.581     1662250.737      300287.297
#Sta/Elev= 28
       0  759.24    49.2  757.13      59  756.36    68.9  756.12    88.6  756.07
   108.2  755.88   127.9  755.53   147.6  754.99   167.3  753.82     187  752.88
   226.3  751.19   234.4  751.03   236.2     751     246  751.18   249.4  751.86
   255.8  753.14   265.7  756.63   275.5  757.95   285.4  760.47   295.2  767.23
     305   776.4   324.7  795.64   344.4  814.49   354.3  823.84   364.1  830.18
   373.9  829.06   383.8  826.82   393.6  825.23
#Mann= 3 , 0 , 0
       0     .06       0   234.4    .045       0   249.4     .06       0
Bank Sta=234.4,249.4
XS Rating Curve= 0 ,0
Exp/Cntr=0.3,0.1

Type RM Length L Ch R = 1 ,1528.2  ,313.2,302.1,291.2
XS GIS Cut Line= 2
     1661980.926      300758.189     1662415.145      300779.398
#Sta/Elev= 30
       0  778.49     9.7  770.01    19.3   764.5      29  759.81    38.6  756.02
    48.3  754.06    96.6  750.61   106.3  749.35   115.9  748.39   135.2  745.76
   144.9  744.77   147.9  744.67   154.6  744.44   162.9  744.67   173.9  745.66
   202.9  750.34   212.5  751.27   289.8  751.66   309.2  751.92   318.8  752.24
   328.5  752.98   338.1  754.47   347.8  756.77   357.4  759.58   367.1  762.67
   376.8  765.98   386.4  770.11   396.1  776.01   425.1  785.23   434.7  788.55
#Mann= 3 , 0 , 0
       0     .08       0   147.9    .045       0   162.9     .08       0
Bank Sta=147.9,162.9
XS Rating Curve= 0 ,0
Exp/Cntr=0.3,0.1

Type RM Length L Ch R = 1 ,1226.1  ,180.6,177,173.4
XS GIS Cut Line= 2
     1662111.598      301104.603     1662512.548      300908.393
#Sta/Elev= 30
       0  840.84     9.7  831.95    19.4  819.01    29.1  810.78    58.2  784.47
    67.9  776.28    77.6  769.21      97  757.95   106.7  751.53   116.4  747.18
   126.2  745.43   145.6  741.25   156.8  740.17     165   740.1   171.8  740.77
   174.7  741.05   184.4  743.15   194.1  744.88   213.5  745.44   320.2  746.18
   329.9  746.68   339.6  748.35   349.3  751.89     359  756.14   368.8  760.47
   388.2  769.72   407.6  777.14   417.3  783.84     427  792.11   446.4  803.06
#Mann= 3 , 0 , 0
       0     .08       0   156.8    .045       0   171.8     .06       0
Bank Sta=156.8,171.8
XS Rating Curve= 0 ,0
Exp/Cntr=0.3,0.1

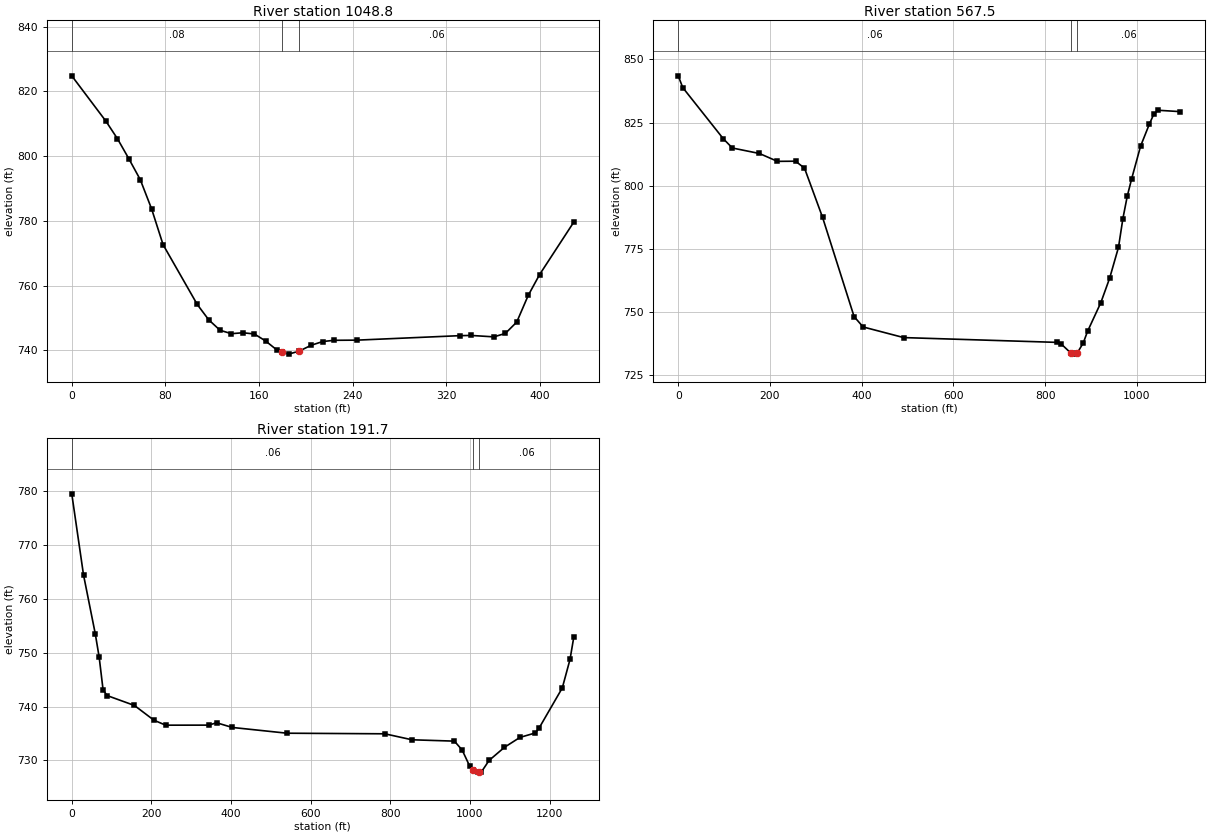
Type RM Length L Ch R = 1 ,1048.8  ,482.3,481.4,480.4
XS GIS Cut Line= 2
     1662184.451      301298.922     1662535.338      301052.351
#Sta/Elev= 30
       0  824.79    29.2  810.77      39  805.39    48.7  799.23    58.5  792.75
    68.2  783.71      78  772.66   107.2   754.2     117  749.46   126.7  746.23
   136.4  745.18   146.2  745.47     156  745.09   165.7   742.9   175.4   740.1
   179.2  739.62   185.2  738.87   194.2  739.79   204.7  741.63   214.4  742.76
   224.2  743.14   243.7  743.19   331.4  744.57   341.1  744.64   360.6   744.2
   370.4  745.27   380.1  748.76   389.9  756.98   399.6  763.41   428.9  779.66
#Mann= 3 , 0 , 0
       0     .08       0   179.2    .045       0   194.2     .06       0
Bank Sta=179.2,194.2
XS Rating Curve= 0 ,0
Exp/Cntr=0.3,0.1

Type RM Length L Ch R = 1 ,567.5   ,373.4,375.7,378
XS GIS Cut Line= 3
     1661821.613      301692.013     1662599.502      301574.718
     1662841.198      301383.703
#Sta/Elev= 30
       0  843.46     9.8  838.82    98.3  818.57     118  814.92     177  812.75
   216.3  809.64   255.7   809.7   275.3  806.97   314.7   787.5   383.5  748.24
   403.2  744.15   491.7  739.95   825.2  738.06   834.8  737.47   855.6  733.92
   863.7  733.41   870.6  734.04     883  737.76   892.6  742.45   921.5  753.77
   940.7  763.44     960  775.65   969.6  787.02   979.2  795.94   988.8  802.82
  1008.1  815.62  1027.4  824.41    1037  828.31  1046.6  829.84  1094.8   829.3
#Mann= 3 , 0 , 0
       0     .06       0   855.6    .045       0   870.6     .06       0
#XS Ineff= 2 , 0
          817.13  738.09
Permanent Ineff=
       F       F
Bank Sta=855.6,870.6
XS Rating Curve= 0 ,0
Exp/Cntr=0.3,0.1

Type RM Length L Ch R = 1 ,191.7   ,188.3,191.6,194.8
XS GIS Cut Line= 3
     1661884.592      302043.644     1662693.432      301937.195
     1663071.726      301702.392
#Sta/Elev= 30
       0  779.46    29.5  764.42      59  753.51    68.8  749.17    78.6  743.12
    88.5  742.04   157.3   740.2   206.4  737.46   235.9  736.54     344  736.55
   363.7  736.99     403  736.12   540.6  735.05   786.3  734.94   854.5  733.83
     961  733.58   980.4  731.94   999.7   728.9  1007.9  728.17  1019.1  727.83
  1022.9  727.85  1028.8  727.87  1048.1     730  1086.8  732.44  1125.6  734.27
  1164.3   735.1  1173.9  736.03    1232  743.45  1251.4  748.75    1261  752.94
#Mann= 3 , 0 , 0
       0     .06       0  1007.9    .045       0  1022.9     .06       0
Bank Sta=1007.9,1022.9
XS Rating Curve= 0 ,0
Exp/Cntr=0.3,0.1

Chan Stop Cuts=-1
Use User Specified Reach Order=0
Composite Channel Slope=5